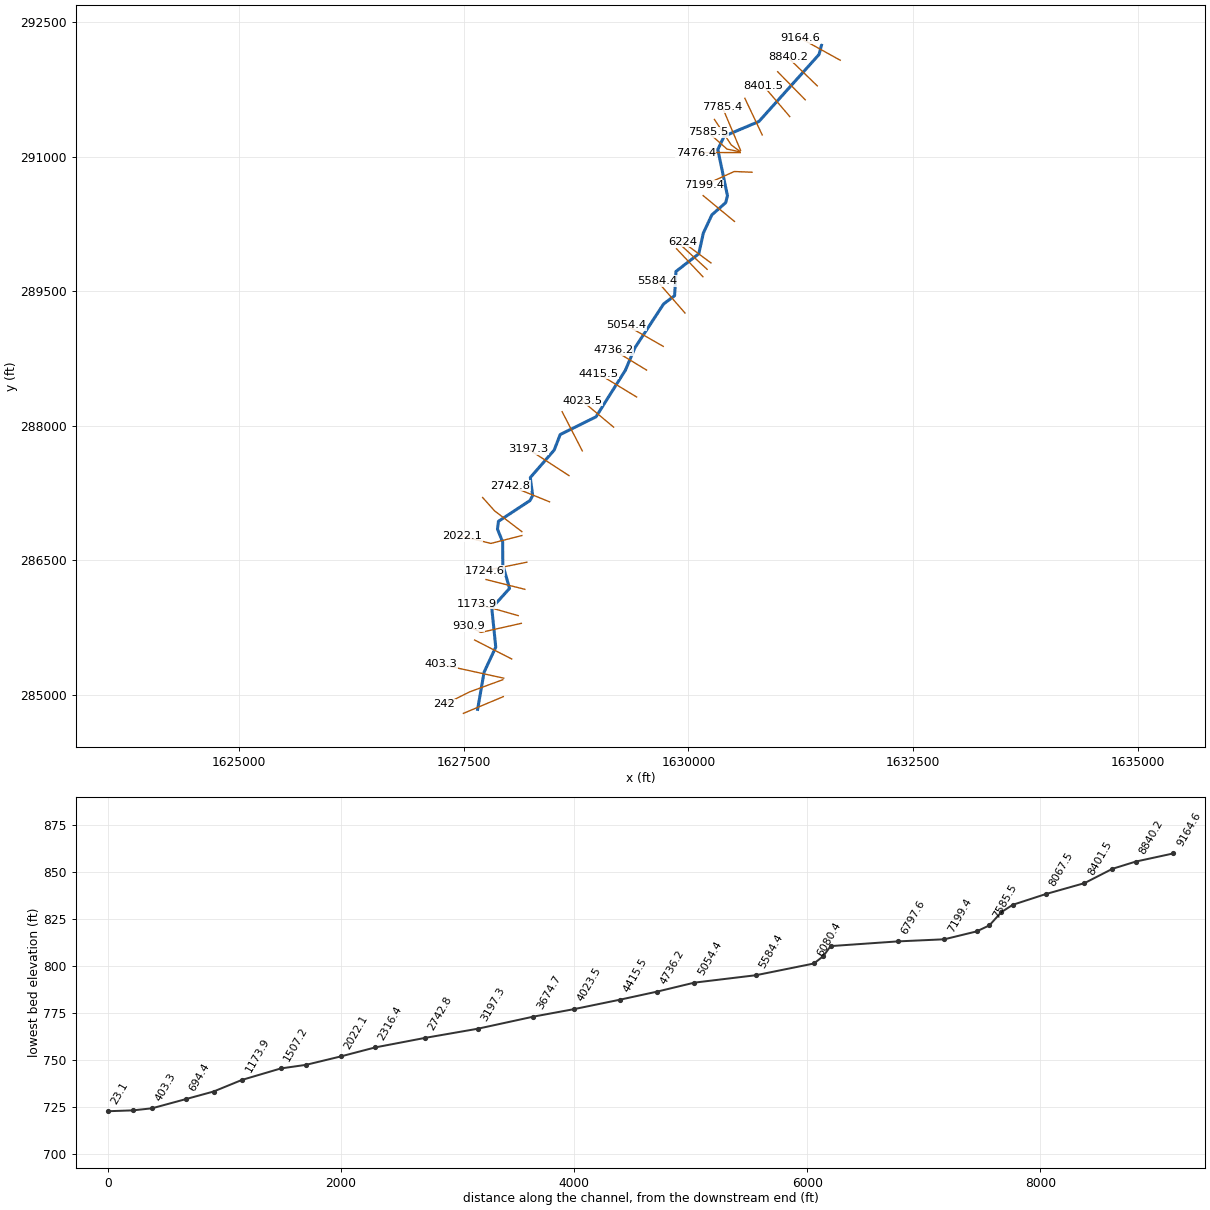
--- rffcrk.prj (project) ---

Proj Title=rffcrk
Current Plan=p01
Default Exp/Contr=0,0
English Units
Geom File=g01
Flow File=f01
Plan File=p01
BEGIN DESCRIPTION:
END DESCRIPTION:
DSS Export Rating Curves= 0
DSS Export Rating Curve Sorted= 0
DSS Export Volume Flow Curves= 0
DXF OffsetX= 0
DXF OffsetY= 0
DXF ScaleX= 0
DXF ScaleY= 0

--- rffcrk.p01 (plan) ---

Plan Title=Approximate Study - 100yr
Program Version=4.00
Geom File=g01
Flow File=f01
Subcritical Flow
K Sum by GR= 0
Std Step Tol= 0.01
Critical Tol= 0.01
Num of Std Step Trials= 20
Max Error Tol= 0.3
Flow Tol Ratio= 0.001
Split Flow NTrial= 30
Split Flow Tol= 0.02
Split Flow Ratio= 0.02
Log Output Level= 0
Friction Slope Method= 1
Unsteady Friction Slope Method= 2
Unsteady Bridges Friction Slope Method= 1
Parabolic Critical Depth
Global Vel Dist= 0 , 0 , 0
Global Log Level= 0
CheckData=True
Encroach Param=-1 ,0,0, 0
Run HTab= 0
Run UNet= 0
Run PostProcess= 0
Run WQNet= 0
UNET Theta= 0
UNET Theta Warmup= 0
UNET ZTol= 0
UNET ZSATol= 0
UNET MxIter= 0
UNET MaxInSteps= 0
UNET DtIC= 0
UNET DtMin= 0
UNET MaxCRTS= 0
UNET WFStab= 0
UNET SFStab= 0
UNET WFX= 1
UNET SFX= 1
UNET DSS MLevel= 1
UNET DZMax Abort= 0
UNET Convert EG Bridges= 0
UNET Use Existing IB Tables= 0
UNET Froude Reduction=False
UNET Froude Limit= 0
UNET Froude Power= 0
UNET Time Slicing=0,0, 5
Write IC File= 0
Echo Input=False
Echo Output=False
Write Detailed= 0
Detailed Automatic Start=False, 0
WQ ULTIMATE=-1
WQ Max Comp Step=1HOUR
WQ Output Interval=15MIN
WQ Output Selected Increments= 0
WQ Output face flow=0
WQ Output face velocity=0
WQ Output face area=0
WQ Output face dispersion=0
WQ Output cell volume=0
WQ Output cell surface area=0
WQ Output cell continuity=0
WQ Output face conc=0
WQ Output face dconc_dx=0
WQ Output face courant=0
WQ Output face peclet=0
WQ Output face adv mass=0
WQ Output face disp mass=0
WQ Output cell mass=0
WQ Output cell source sink temp=0
WQ Output cell source sink nsm=0
WQ Output MaxMinRange=-1
WQ Daily Max Min Mean=-1
WQ Daily Range=0
WQ Daily Time=0
WQ Create Restart=0
WQ Fixed Restart=0
WQ System Summary=False
Sorting and Armoring Iterations= 10
XS Update Threshold= 0.02
Hydraulics Update Threshold= 0.02
Energy Slope Method= 1
Volume Change Method= 0
XS Weighting Method= 0
Number of US Weighted Cross Sections= 1
Number of DS Weighted Cross Sections= 1
Upstream XS Weight=0.25
Main XS Weight=0.5
Downstream XS Weight=0.25
Number of DS XS's Weighted with US Boundary= 1
Upstream Boundary Weight= 1
Weight of XSs Associated with US Boundary= 0
Number of US XS's Weighted with DS Boundary= 1
Downstream Boundary Weight= 0.5
Weight of XSs Associated with DS Boundary= 0.5
Sediment Output Level= 4
Mass or Volume Output= 0
Output Increment Type= 1
Profile and TS Output Increment= 10
XS Output Flag= 0
XS Output Increment= 10
Disregard all LS=0
Disregard all Conn=0
Disregard all Breaches=0
Disregard all Pumps=0

--- rffcrk.f01 (steady flow) ---

Flow Title=USGS Regression Equation
Program Version=4.00
Number of Profiles= 1
Profile Names=P100yr
River Rch & RM=rffcrk,Main            ,9164.6
     394
River Rch & RM=rffcrk,Main            ,7785.4
     422
River Rch & RM=rffcrk,Main            ,7476.4
     700
River Rch & RM=rffcrk,Main            ,5584.4
     730
River Rch & RM=rffcrk,Main            ,2742.8
     806
River Rch & RM=rffcrk,Main            ,242
     862
Boundary for River Rch & Prof#=rffcrk,Main            , 1
Up Type= 0
Dn Type= 3
Dn Slope=0.008595
DSS Import GetInterval= 0
DSS Import GetPeak= 0
DSS Import FillOption= 0

--- rffcrk.g01 (geometry) ---

Geom Title=USGS 3m DEM
Program Version=4.00

River Reach=rffcrk          ,Main
Reach XY= 30
     1631481.225      292241.712     1631454.206       292139.33
     1630785.639      291392.421     1630398.779       291228.02
     1630327.868      291079.228     1630435.302      290563.857
     1630415.336       290486.58     1630261.948      290351.405
     1630166.942      290147.732     1630115.816        289916.4
     1629862.631      289720.466     1629847.148      289450.041
     1629724.766      289357.699     1629406.252      288869.814
     1629299.883       288619.16      1628972.81      288099.522
     1628574.374      287901.779     1628507.594      287728.704
     1628242.125      287422.751     1628267.857      287220.969
     1628238.527      287166.155     1627887.363      286934.429
     1627876.654      286846.718      1627934.68       286704.23
     1627935.497      286452.217     1628010.511      286186.198
     1627813.141      285967.352     1627857.509      285531.829
     1627727.638      285252.665     1627655.621       284837.89

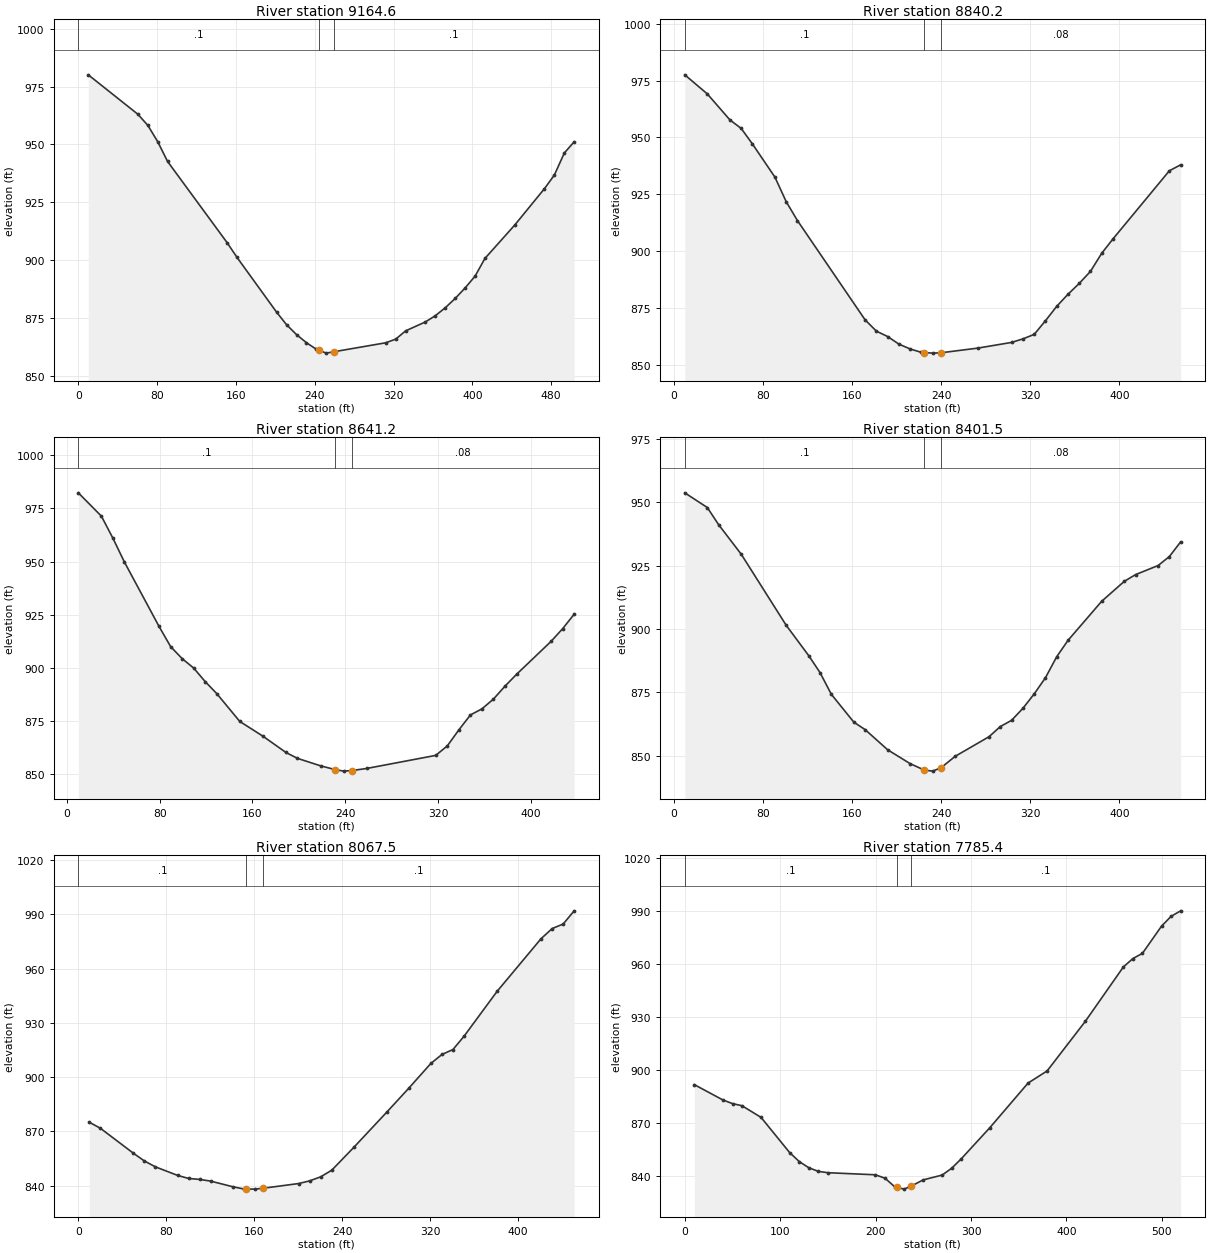
Type RM Length L Ch R = 1 ,9164.6  ,330.3,324.4,318.6
XS GIS Cut Line= 2
     1631689.969      292074.967     1631249.695      292319.119
#Sta/Elev= 30
    10.1  980.05    60.4  963.03    70.5  958.24    80.6  951.15    90.6  942.61
     151  907.55   161.1  901.15   201.4  877.42   211.4  872.05   221.5  867.79
   231.6  864.27   241.7  861.43   244.2  861.02   251.7  859.77   259.2  860.35
   312.1  864.24   322.2  865.81   332.3  869.39   352.4  873.26   362.5  875.95
   372.5  879.37   382.6  883.39   392.7  887.95   402.8  893.03   412.8  900.69
     443  915.09   473.2  930.83   483.3  936.73   493.4  946.26   503.4  951.11
#Mann= 3 , 0 , 0
       0      .1       0   244.2    .045       0   259.2      .1       0
Bank Sta=244.2,259.2
XS Rating Curve= 0 ,0
Exp/Cntr=0.3,0.1

Type RM Length L Ch R = 1 ,8840.2  ,199.6,199,198.5
XS GIS Cut Line= 2
     1631434.316      291789.342     1631107.734      292106.152
#Sta/Elev= 30
    10.1  977.49    30.3  969.12    50.6  957.71    60.7  953.98    70.8  947.16
      91  932.59   101.1  921.84   111.2  913.54   171.9     870     182  865.06
   192.1  862.69   202.2  859.37   212.3  857.24   222.4  855.74   225.1  855.65
   232.6  855.41   240.1  855.57     273  857.61   303.3  860.11   313.4  861.64
   323.6  863.62   333.7   869.6   343.8  875.93   353.9  881.21     364  885.98
   374.1  891.27   384.2  899.21   394.3  905.51   444.9  935.41     455  938.01
#Mann= 3 , 0 , 0
    10.1      .1       0   225.1    .045       0   240.1     .08       0
Bank Sta=225.1,240.1
XS Rating Curve= 0 ,0
Exp/Cntr=0.3,0.1

Type RM Length L Ch R = 1 ,8641.2  ,241.3,239.7,238.1
XS GIS Cut Line= 2
     1631300.238       291634.28     1630993.985      291946.618
#Sta/Elev= 30
     9.9  982.35    29.8  971.38    39.8  960.93    49.7  949.76    79.5  919.56
    89.5  910.08    99.4  904.45   109.4  899.99   119.3  893.63   129.2  888.04
   149.1  874.93     169  868.02   188.9  860.35   198.8  857.59   218.7  854.08
   231.1  852.33   238.6  851.58   246.1  851.87   258.5  852.83   318.1  858.98
   328.1  863.48     338  870.97     348     878   357.9  880.84   367.8  885.43
   377.8  891.52   387.7  897.05   417.5  912.55   427.5  918.53   437.4  925.32
#Mann= 3 , 0 , 0
     9.9      .1       0   231.1    .045       0   246.1     .08       0
Bank Sta=231.1,246.1
XS Rating Curve= 0 ,0
Exp/Cntr=0.3,0.1

Type RM Length L Ch R = 1 ,8401.5  ,340.1,334,327.8
XS GIS Cut Line= 2
     1631128.246      291447.021      1630833.02      291793.238
#Sta/Elev= 30
    10.1  953.74    30.3  947.94    40.4  941.21    60.7  929.55   101.1  901.48
   121.3  889.52   131.4  882.86   141.6  874.27   161.8  863.27   171.9  860.35
   192.1   852.4   212.3  846.92   225.1  844.37   232.6  843.97   240.1  845.33
   252.8  849.84   283.1  857.55   293.2  861.55   303.3     864   313.4  868.69
   323.6  874.42   333.7  880.79   343.8  889.08   353.9  895.52   384.2  910.98
   404.4  918.81   414.6  921.49   434.8  925.06   444.9  928.61     455  934.38
#Mann= 3 , 0 , 0
    10.1      .1       0   225.1    .045       0   240.1     .08       0
Bank Sta=225.1,240.1
XS Rating Curve= 0 ,0
Exp/Cntr=0.3,0.1

Type RM Length L Ch R = 1 ,8067.5  ,283.1,282.1,281.1
XS GIS Cut Line= 2
      1630821.59      291242.844     1630628.914      291650.505
#Sta/Elev= 30
      10  875.08      20  871.78    50.1  857.95    60.1  853.67    70.1  850.43
    90.2  845.72   100.2  844.03   110.2  843.49   120.2  842.57   140.3  839.46
   150.3  838.23   152.8   838.2   160.3  838.12   167.8  838.59   200.4  841.21
   210.4   842.7   220.4  844.92   230.5   848.6   250.5  861.19   280.6  880.74
   300.6  893.95   320.6  907.58   330.7  912.54   340.7  915.28   350.7  922.56
   380.8  947.41   420.8  976.52   430.9  982.12   440.9  984.62   450.9  991.92
#Mann= 3 , 0 , 0
       0      .1       0   152.8    .045       0   167.8      .1       0
Bank Sta=152.8,167.8
XS Rating Curve= 0 ,0
Exp/Cntr=0.3,0.1

Type RM Length L Ch R = 1 ,7785.4  ,92.5,96.6,100.8
XS GIS Cut Line= 2
     1630581.279      291070.342      1630379.45      291549.097
#Sta/Elev= 30
      10  891.62      40  882.92      50  880.88    59.9  879.68    79.9  873.08
   109.9  853.12   119.9  848.07   129.9  844.55   139.9   842.5   149.9  841.73
   199.8  840.55   209.8   838.6   219.8  833.87   222.3  833.51   229.8  832.43
   237.3  834.15   249.8  837.67   269.8  840.41   279.8  844.33   289.8  849.65
   319.7  867.25   359.7   892.5   379.7  899.39   419.6  927.39   459.6  958.29
   469.6  963.04   479.6  966.01   499.6   981.4   509.6  986.96   519.6  990.08
#Mann= 3 , 0 , 0
       0      .1       0   222.3    .045       0   237.3      .1       0
Bank Sta=222.3,237.3
XS Rating Curve= 0 ,0
Exp/Cntr=0.3,0.1

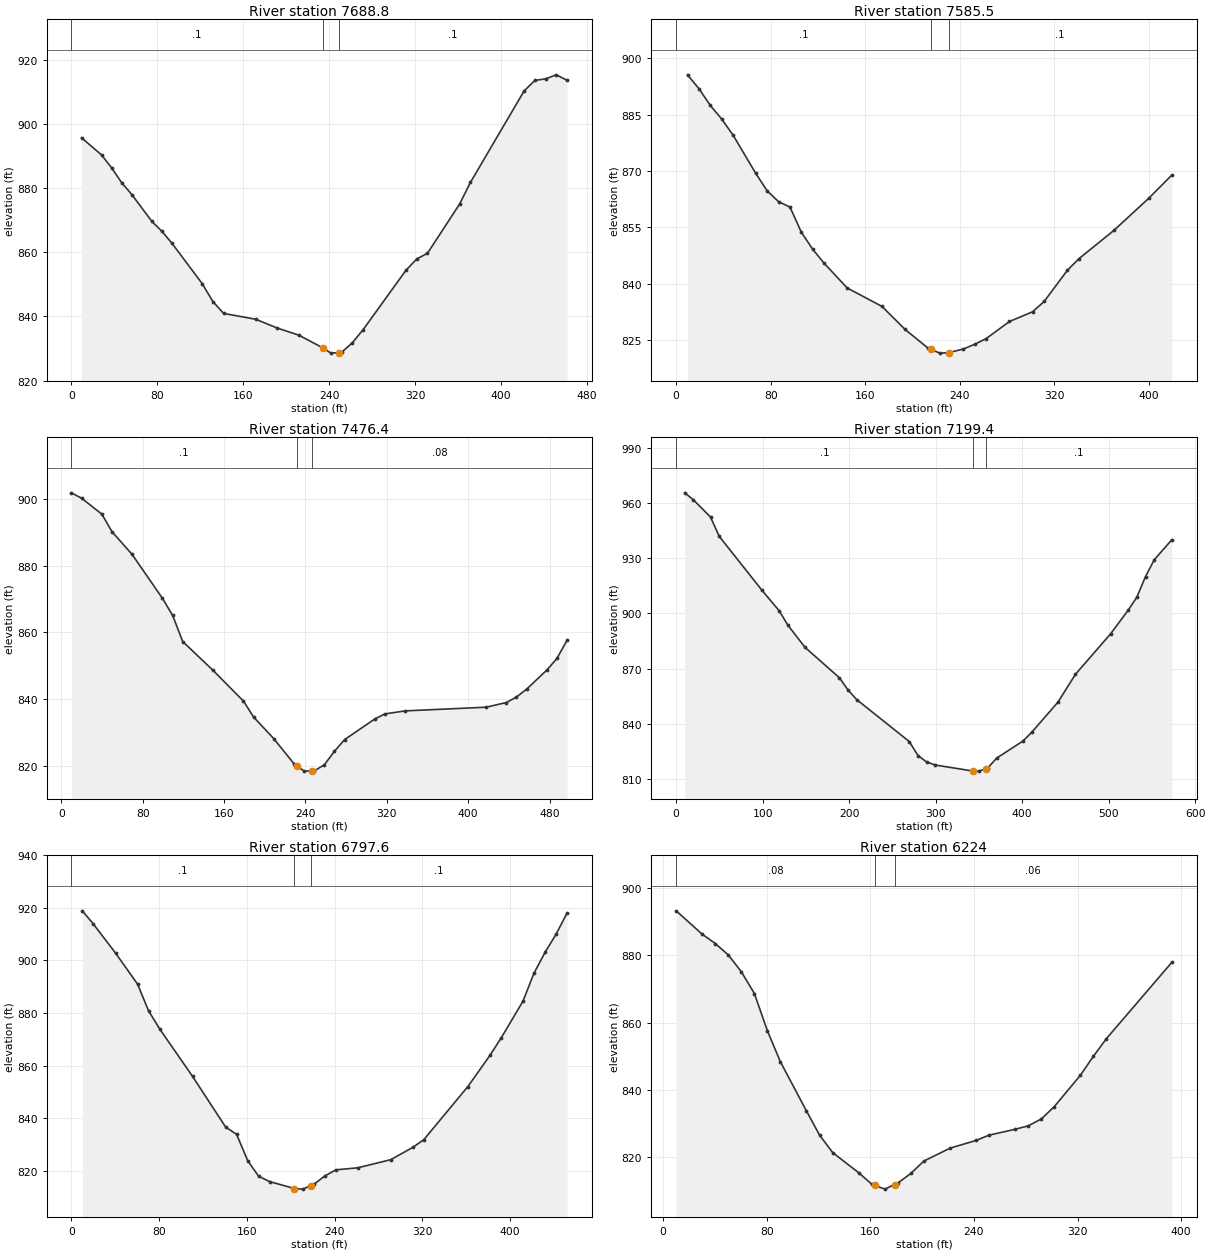
Type RM Length L Ch R = 1 ,7688.8  ,96.8,103.3,109.4
XS GIS Cut Line= 3
     1630574.154       291058.28     1630476.802      291131.294
     1630290.211      291415.238
#Sta/Elev= 30
     9.4  895.68    28.1  890.31    37.4  886.31    46.8  881.67    56.2  877.99
    74.9  869.61    84.2  866.54    93.6   862.8   121.7  850.24   131.7  844.64
   141.7  840.93   171.7   839.1   191.6  836.37   211.6  834.17   234.1   830.2
   241.6  828.55   249.1  828.74   251.6   828.8   261.6  831.78   271.6  835.86
   311.6  854.41   321.6  857.92   331.5  859.65   361.5  875.04   371.5  881.74
   421.5  910.25   431.5  913.55   441.5  914.05   451.5   915.3   461.5   913.6
#Mann= 3 , 0 , 0
       0      .1       0   234.1    .045       0   249.1      .1       0
Bank Sta=234.1,249.1
XS Rating Curve= 0 ,0
Exp/Cntr=0.3,0.1

Type RM Length L Ch R = 1 ,7585.5  ,92.4,109.2,127.5
XS GIS Cut Line= 3
     1630561.985      291056.252     1630430.154      291084.647
     1630217.196      291273.266
#Sta/Elev= 30
     9.6  895.58    19.3  891.89    28.9  887.42    38.5  883.82    48.2   879.5
    67.4  869.32    77.1  864.65    86.7  861.81    96.3  860.38     106  853.62
   115.6  849.12   125.2  845.43   144.7  838.85   174.1  833.95   193.7  827.81
   213.3  822.79   215.6  822.49   223.1  821.51   230.6  821.64   242.8  822.59
   252.6  823.87   262.4   825.4     282  829.93   301.6  832.52   311.4  835.28
     331  843.56   340.9  846.68   370.3  854.16   399.7  862.68   419.3  868.88
#Mann= 3 , 0 , 0
       0      .1       0   215.6    .045       0   230.6      .1       0
Bank Sta=215.6,230.6
XS Rating Curve= 0 ,0
Exp/Cntr=0.3,0.1

Type RM Length L Ch R = 1 ,7476.4  ,267.3,276.9,286.6
XS GIS Cut Line= 2
     1630578.216      291045.506     1630080.968      291046.327
#Sta/Elev= 30
     9.9  901.89    19.9  900.27    39.8  895.49    49.7  890.24    69.6  883.37
    99.4   870.2   109.4  865.06   119.3  857.24   149.2  848.55     179  839.35
     189  834.56   208.8  828.08   228.7  820.54   231.2  819.98   238.7  818.31
   246.2  818.35   248.6  818.36   258.6  820.22   268.5  824.27   278.5  827.78
   308.3  833.99   318.2   835.5   338.1   836.4   417.7  837.51   437.6  838.92
   447.5  840.57   457.5  842.93   477.4  848.67   487.3  852.16   497.2  857.61
#Mann= 3 , 0 , 0
     9.9      .1       0   231.2    .045       0   246.2     .08       0
Bank Sta=231.2,246.2
XS Rating Curve= 0 ,0
Exp/Cntr=0.3,0.1

Type RM Length L Ch R = 1 ,7199.4  ,427.3,401.8,376.3
XS GIS Cut Line= 3
     1630709.359       290826.19     1630510.901      290834.521
     1630169.911      290679.931
#Sta/Elev= 30
     9.9  965.66    19.9  961.87    39.7  952.48    49.7  942.02    99.3  912.54
   119.2   901.4   129.1  893.63     149  881.51   188.7  864.98   198.6  858.38
   208.8  853.03   269.5  830.25   279.6  822.62   289.7  819.05   299.8  817.43
   342.9  814.19   350.4  814.12   357.9  815.55   360.5  816.04   370.7  821.25
     401  830.51   411.1  835.26   441.5  851.72   461.7  866.88   502.2  888.83
   522.4  901.59   532.6   908.8   542.7  920.09   552.8  929.23     573  940.06
#Mann= 3 , 0 , 0
       0      .1       0   342.9    .045       0   357.9      .1       0
Bank Sta=342.9,357.9
XS Rating Curve= 0 ,0
Exp/Cntr=0.3,0.1

Type RM Length L Ch R = 1 ,6797.6  ,572.6,573.6,574.3
XS GIS Cut Line= 2
     1630513.237      290277.849     1630164.743      290565.691
#Sta/Elev= 30
      10  918.84    20.1  913.75    40.2  902.79    60.3  890.97    70.3  880.85
    80.4  873.96   110.5  855.84   140.6  836.62   150.7  833.79   160.7  823.85
   170.8  817.85   180.8  815.86   203.4   813.2   210.9  812.99   218.4  814.31
     221  814.77     231  817.97   241.1  820.32   261.2  821.11   291.3   824.2
   311.4  828.89   321.4  831.81   361.6  852.02   381.7  863.85   391.7  870.33
   411.8  884.45   421.9  895.15   431.9     903     442  909.94     452  917.97
#Mann= 3 , 0 , 0
       0      .1       0   203.4    .045       0   218.4      .1       0
Bank Sta=203.4,218.4
XS Rating Curve= 0 ,0
Exp/Cntr=0.3,0.1

Type RM Length L Ch R = 1 ,6224    ,65.8,63.5,61.4
XS GIS Cut Line= 2
     1630251.675      289815.014     1629936.879      290049.707
#Sta/Elev= 30
    10.1  893.27    30.2  886.32    40.3  883.55    50.3  880.17    60.4  875.16
    70.5  868.67    80.5  857.62    90.6  848.34   110.7  833.75   120.8  826.57
   130.9  821.38     151  815.38   161.1  811.97   163.7  811.59   171.2   810.5
   178.7  811.85   181.2   812.3   191.3  815.17   201.4  818.86   221.5  822.68
   241.6  824.98   251.7  826.56   271.8   828.3   281.9  829.33     292  831.36
     302  835.03   322.2  844.38   332.2  850.01   342.3  855.28   392.7  877.92
#Mann= 3 , 0 , 0
    10.1     .08       0   163.7    .045       0   178.7     .06       0
Bank Sta=163.7,178.7
XS Rating Curve= 0 ,0
Exp/Cntr=0.3,0.1

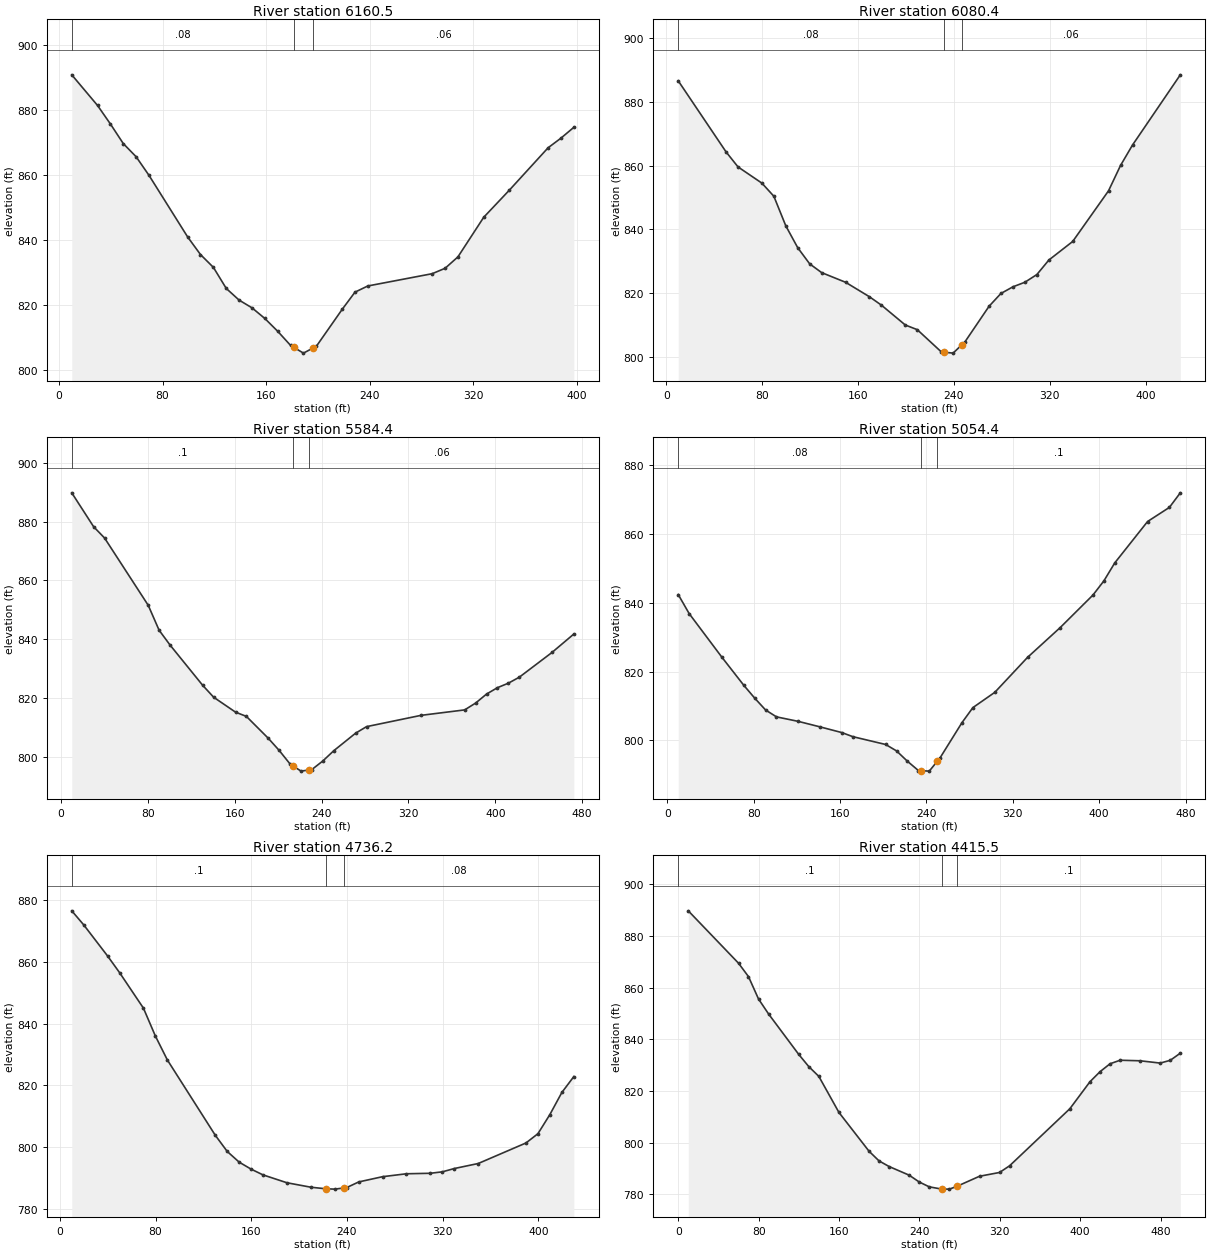
Type RM Length L Ch R = 1 ,6160.5  ,81.7,80.1,78.6
XS GIS Cut Line= 2
     1630209.084      289744.028     1629917.028      290013.774
#Sta/Elev= 30
     9.9  890.86    29.8  881.42    39.8  875.68    49.7  869.67    59.6  865.62
    69.6  859.85    99.4   840.9   109.3  835.49   119.3  831.52   129.2  825.05
   139.1  821.46   149.1  819.07     159  815.79     169  811.82   178.9  807.48
   181.3  806.91   188.8  805.12   196.3  806.71   198.8  807.24   218.7   818.6
   228.6  823.91   238.5  825.81   288.2  829.59   298.2  831.26   308.1  834.78
     328  846.97   347.9  855.37   377.7  868.38   387.6  871.34   397.6  874.69
#Mann= 3 , 0 , 0
     9.9     .08       0   181.3    .045       0   196.3     .06       0
Bank Sta=181.3,196.3
XS Rating Curve= 0 ,0
Exp/Cntr=0.3,0.1

Type RM Length L Ch R = 1 ,6080.4  ,497,496,495
XS GIS Cut Line= 2
     1630162.436      289660.873     1629868.352      289973.211
#Sta/Elev= 30
      10   886.6    49.9  864.33    59.9  859.61    79.8  854.54    89.8  850.42
    99.8  841.12   109.7   834.3   119.7  829.23   129.7  826.48   149.7  823.45
   169.6  818.91   179.6  816.28   199.5  810.06   209.5   808.6   229.5  801.65
   231.9  801.55   239.4  801.25   246.9  803.95   249.4  804.85   269.4  815.94
   279.3  819.95   289.3  822.03   299.3  823.47   309.3  825.88   319.3  830.43
   339.2  836.25   369.1  852.13   379.1  860.06   389.1  866.47     429  888.48
#Mann= 3 , 0 , 0
      10     .08       0   231.9    .045       0   246.9     .06       0
Bank Sta=231.9,246.9
XS Rating Curve= 0 ,0
Exp/Cntr=0.3,0.1

Type RM Length L Ch R = 1 ,5584.4  ,522.5,530,537.6
XS GIS Cut Line= 2
     1629962.609      289257.005     1629652.702      289613.435
#Sta/Elev= 30
      10  889.88    30.1  878.34    40.2  874.48    80.4  851.55    90.4  843.07
   100.5     838   130.6  824.25   140.7   820.2   160.8  815.13   170.8  813.68
   190.9  806.24     201  802.08     211  797.46   213.6  796.84   221.1  795.03
   228.6  795.44   231.1  795.58   241.2   798.5   251.2  801.97   271.3  807.95
   281.4  810.19   331.6  814.04   371.8   815.9   381.9  818.24   391.9  821.29
     402  823.48     412     825   422.1  827.05   452.2  835.48   472.3  841.76
#Mann= 3 , 0 , 0
      10      .1       0   213.6    .045       0   228.6     .06       0
Bank Sta=213.6,228.6
XS Rating Curve= 0 ,0
Exp/Cntr=0.3,0.1

Type RM Length L Ch R = 1 ,5054.4  ,318.7,318.1,317.6
XS GIS Cut Line= 2
     1629720.744      288884.982     1629308.488      289121.129
#Sta/Elev= 30
    10.1  842.36    20.2  836.84    50.5  824.17    70.8  816.01    80.9  812.28
      91  808.83   101.1  806.83   121.3  805.52   141.5  803.92   161.7  802.26
   171.8  801.08   202.2  798.81   212.3  796.94   222.4  793.93   232.5  791.25
   235.1   791.2   242.6  791.07   250.1  793.97   252.7  794.98   272.9  805.16
     283  809.52   303.3  813.96   333.6  824.11   363.9  832.78   394.2  842.22
   404.3  846.32   414.4  851.56   444.8  863.58     465  867.68   475.1  871.91
#Mann= 3 , 0 , 0
    10.1     .08       0   235.1    .045       0   250.1      .1       0
Bank Sta=235.1,250.1
XS Rating Curve= 0 ,0
Exp/Cntr=0.3,0.1

Type RM Length L Ch R = 1 ,4736.2  ,320.7,320.7,320.7
XS GIS Cut Line= 2
     1629535.732      288620.423     1629168.634      288843.521
#Sta/Elev= 30
      10  876.56      20     872      40  861.88      50  856.49    69.9  844.99
    79.9  835.94    89.9  828.19   129.9   803.8   139.9  798.54   149.9  795.06
   159.8  792.81   169.8  790.93   189.8  788.38   209.8  786.93   222.3  786.42
   229.8  786.31   237.3  786.69   239.8  786.82   249.8  788.64   269.7  790.34
   289.7  791.29   309.7  791.45   319.7  791.92   329.7  792.99   349.7  794.62
   389.6  801.28   399.6  804.29   409.6  810.51   419.6  817.67   429.6  822.82
#Mann= 3 , 0 , 0
      10      .1       0   222.3    .045       0   237.3     .08       0
Bank Sta=222.3,237.3
XS Rating Curve= 0 ,0
Exp/Cntr=0.3,0.1

Type RM Length L Ch R = 1 ,4415.5  ,395.6,392,388.5
XS GIS Cut Line= 2
      1629424.56      288320.631     1628997.742      288580.309
#Sta/Elev= 30
      10  889.68      60  869.41    69.9  864.23    79.9  855.56    89.9  849.77
   119.9  834.13   129.9  829.41   139.9  825.63   159.9  811.68   189.9  796.65
   199.8  792.93   209.8  790.75   229.8   787.4   239.8  784.76   249.8  782.88
   262.3  782.01   269.8     782   277.3  783.08   299.8  786.98   319.7  788.44
   329.7  791.02   389.7  813.11   409.7  823.55   419.7  827.43   429.7  830.51
   439.7  831.87   459.6  831.66   479.6  830.77   489.6  831.84   499.6   834.6
#Mann= 3 , 0 , 0
       0      .1       0   262.3    .045       0   277.3      .1       0
Bank Sta=262.3,277.3
XS Rating Curve= 0 ,0
Exp/Cntr=0.3,0.1

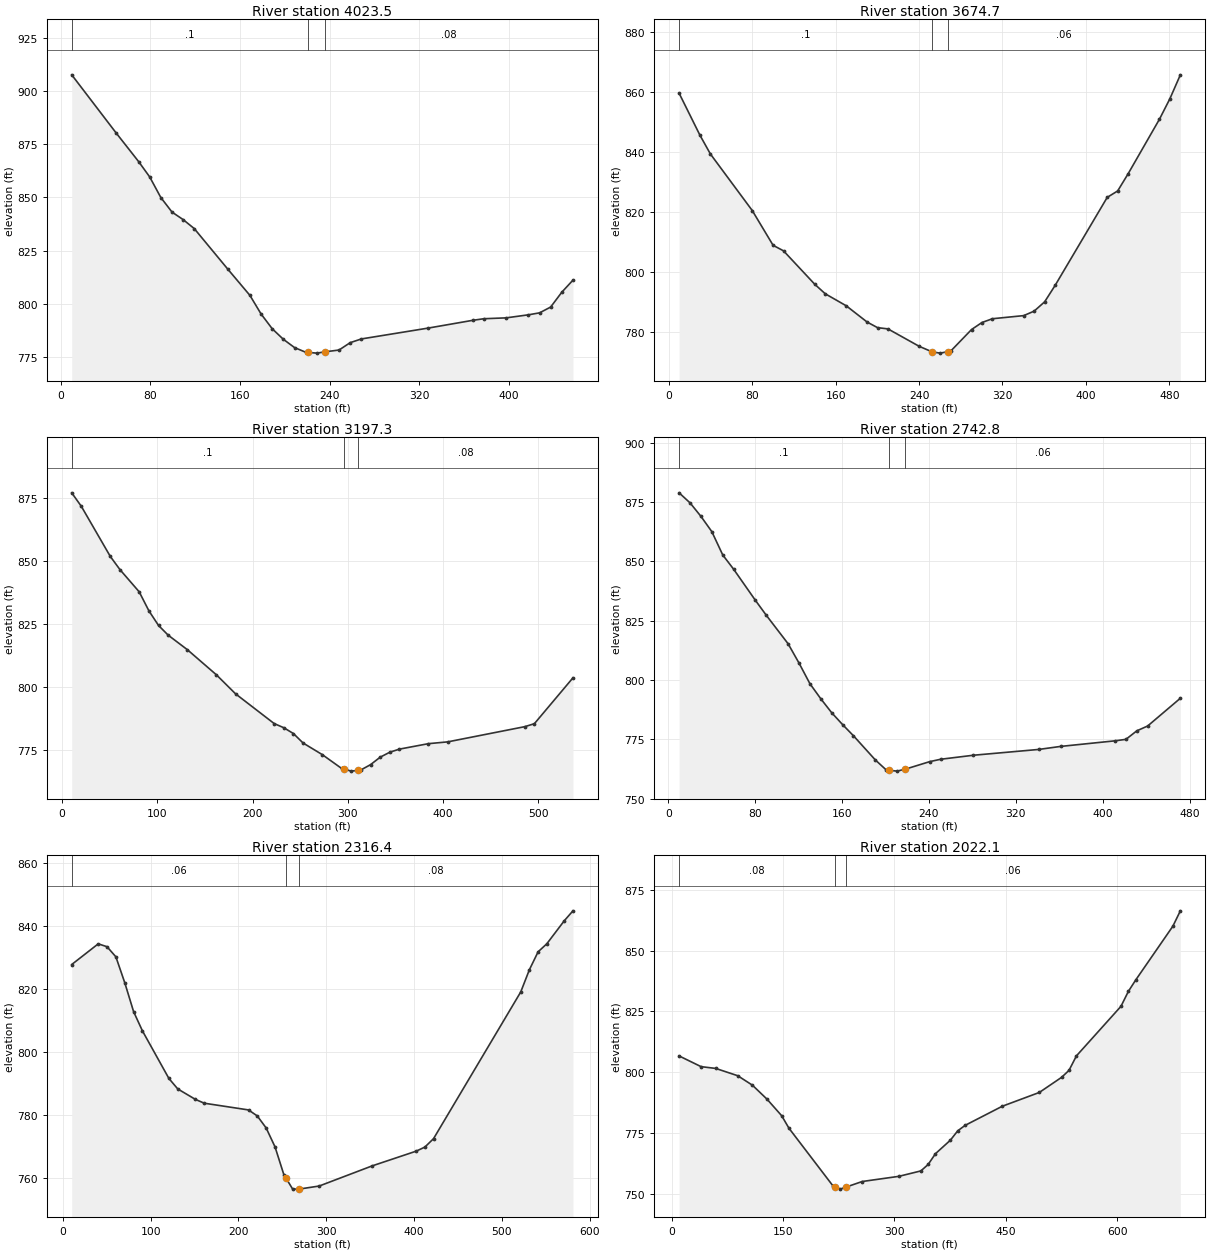
Type RM Length L Ch R = 1 ,4023.5  ,358,348.8,339.6
XS GIS Cut Line= 2
     1629168.566      287984.334     1628818.058      288277.753
#Sta/Elev= 30
     9.9  907.52    49.7  880.14    69.6  866.82    79.5  859.61    89.4  849.97
    99.4  843.14   109.3  839.62   119.2  835.42   149.1  816.42   168.9  804.07
   178.9  795.31   188.8  788.42   198.7  783.49   208.7   779.6   218.6  777.43
   221.1  777.32   228.6     777   236.1  777.62   248.4  778.46   258.4  781.92
   268.3  783.65   327.9  788.74   367.7  792.39   377.6  793.13   397.5  793.54
   417.4  794.97   427.3  795.89   437.2  798.61   447.2   805.6   457.1  811.23
#Mann= 3 , 0 , 0
     9.9      .1       0   221.1    .045       0   236.1     .08       0
Bank Sta=221.1,236.1
XS Rating Curve= 0 ,0
Exp/Cntr=0.3,0.1

Type RM Length L Ch R = 1 ,3674.7  ,465,477.3,489.6
XS GIS Cut Line= 2
     1628820.184      287720.257     1628596.045      288156.529
#Sta/Elev= 30
      10  859.69      30  845.66      40  839.42    80.1  820.57   100.1  808.97
   110.1  807.12   140.1  795.95   150.1   792.8   170.2   788.8   190.2  783.38
   200.2  781.51   210.2  781.09   240.2  775.27   252.8   773.4   260.3  773.01
   267.8  773.51   270.3  773.67   290.3  780.87   300.3  783.22   310.3  784.48
   340.3  785.52   350.3  787.01   360.4  790.12   370.4  795.57   420.4  824.96
   430.4   827.1   440.4  832.81   470.5  851.05   480.5  857.88   490.5  865.83
#Mann= 3 , 0 , 0
      10      .1       0   252.8    .045       0   267.8     .06       0
Bank Sta=252.8,267.8
XS Rating Curve= 0 ,0
Exp/Cntr=0.3,0.1

Type RM Length L Ch R = 1 ,3197.3  ,451.3,454.5,457.7
XS GIS Cut Line= 2
     1628672.092      287444.086     1628222.895       287736.91
#Sta/Elev= 30
    10.1  876.94    20.2  871.57    50.6  851.71    60.7   846.5    80.9  837.69
    91.1  830.15   101.2  824.35   111.3  820.51   131.5  814.73   161.9  804.79
   182.1  797.22   222.6  785.44   232.7  783.79   242.8  781.48   252.9  777.74
   273.2   773.1   293.4  767.64     296  767.37   303.5  766.58     311  766.93
   313.6  767.05   323.8  769.16   333.9  772.12     344  774.09   354.1  775.31
   384.5  777.47   404.7  778.18   485.6  784.21   495.7  785.39   536.2  803.58
#Mann= 3 , 0 , 0
    10.1      .1       0     296    .045       0     311     .08       0
Bank Sta=296,311
XS Rating Curve= 0 ,0
Exp/Cntr=0.3,0.1

Type RM Length L Ch R = 1 ,2742.8  ,430.8,426.4,421.6
XS GIS Cut Line= 2
     1628455.957      287151.904     1628019.071      287329.071
#Sta/Elev= 30
      10  878.85    20.1   874.6    30.1  868.93    40.1  862.51    50.2  852.66
    60.2  846.68    80.2   833.6    90.3  827.26   110.3  815.32   120.4  807.15
   130.4  798.49   140.4  792.15   150.5  786.24   160.5  781.26   170.5  776.56
   190.6   766.4   200.6   762.2   203.1  762.07   210.6  761.68   218.1  762.49
   240.7  765.68   250.8  766.68   280.9  768.37     341  770.81   361.1  772.08
   411.3  774.44   421.3  775.06   431.3  778.64   441.3  780.68   471.4  792.36
#Mann= 3 , 0 , 0
      10      .1       0   203.1    .045       0   218.1     .06       0
Bank Sta=203.1,218.1
XS Rating Curve= 0 ,0
Exp/Cntr=0.3,0.1

Type RM Length L Ch R = 1 ,2316.4  ,274.3,294.3,314.7
XS GIS Cut Line= 3
     1628147.766      286819.697     1627843.576      287051.842
     1627711.494      287199.934
#Sta/Elev= 30
    10.1  827.79    40.3  834.34    50.3  833.43    60.4  830.23    70.5  822.04
    80.6  812.85    90.6  806.79   120.8  791.69   130.9  788.37     151  785.06
   161.1  783.85   211.5  781.72   221.5  779.81   231.6     776   241.7  770.01
   251.7  761.26   254.3  760.07   261.8  756.63   269.3  756.65     292  757.61
   352.4     764   402.5  768.66   412.4  769.95   422.3  772.63   521.6  819.09
   531.5  826.16   541.4  831.82   551.3  834.35   571.2  841.65   581.1   844.8
#Mann= 3 , 0 , 0
    10.1     .06       0   254.3    .045       0   269.3     .08       0
Bank Sta=254.3,269.3
XS Rating Curve= 0 ,0
Exp/Cntr=0.3,0.1

Type RM Length L Ch R = 1 ,2022.1  ,298.6,297.5,296.4
XS GIS Cut Line= 3
     1628147.766       286775.67     1627803.454      286687.999
     1627483.352      286767.665
#Sta/Elev= 30
     9.9   806.7    39.5  802.29    59.2  801.56    88.8  798.56   108.6  794.67
   128.3  788.91     148  782.11   157.9  776.93   217.1  753.22   219.5  752.89
     227  751.86   234.5  752.67   256.6     755     306  757.13   335.6  759.36
   345.4  762.01   355.3  766.46   375.3  771.99   385.3  775.88   395.3  778.13
   445.3  785.99   495.2  791.67   525.2  797.89   535.2  800.77   545.2  806.73
   605.2  827.13   615.2   833.3   625.2  838.04   675.2  860.16   685.2  866.45
#Mann= 3 , 0 , 0
     9.9     .08       0   219.5    .045       0   234.5     .06       0
Bank Sta=219.5,234.5
XS Rating Curve= 0 ,0
Exp/Cntr=0.3,0.1

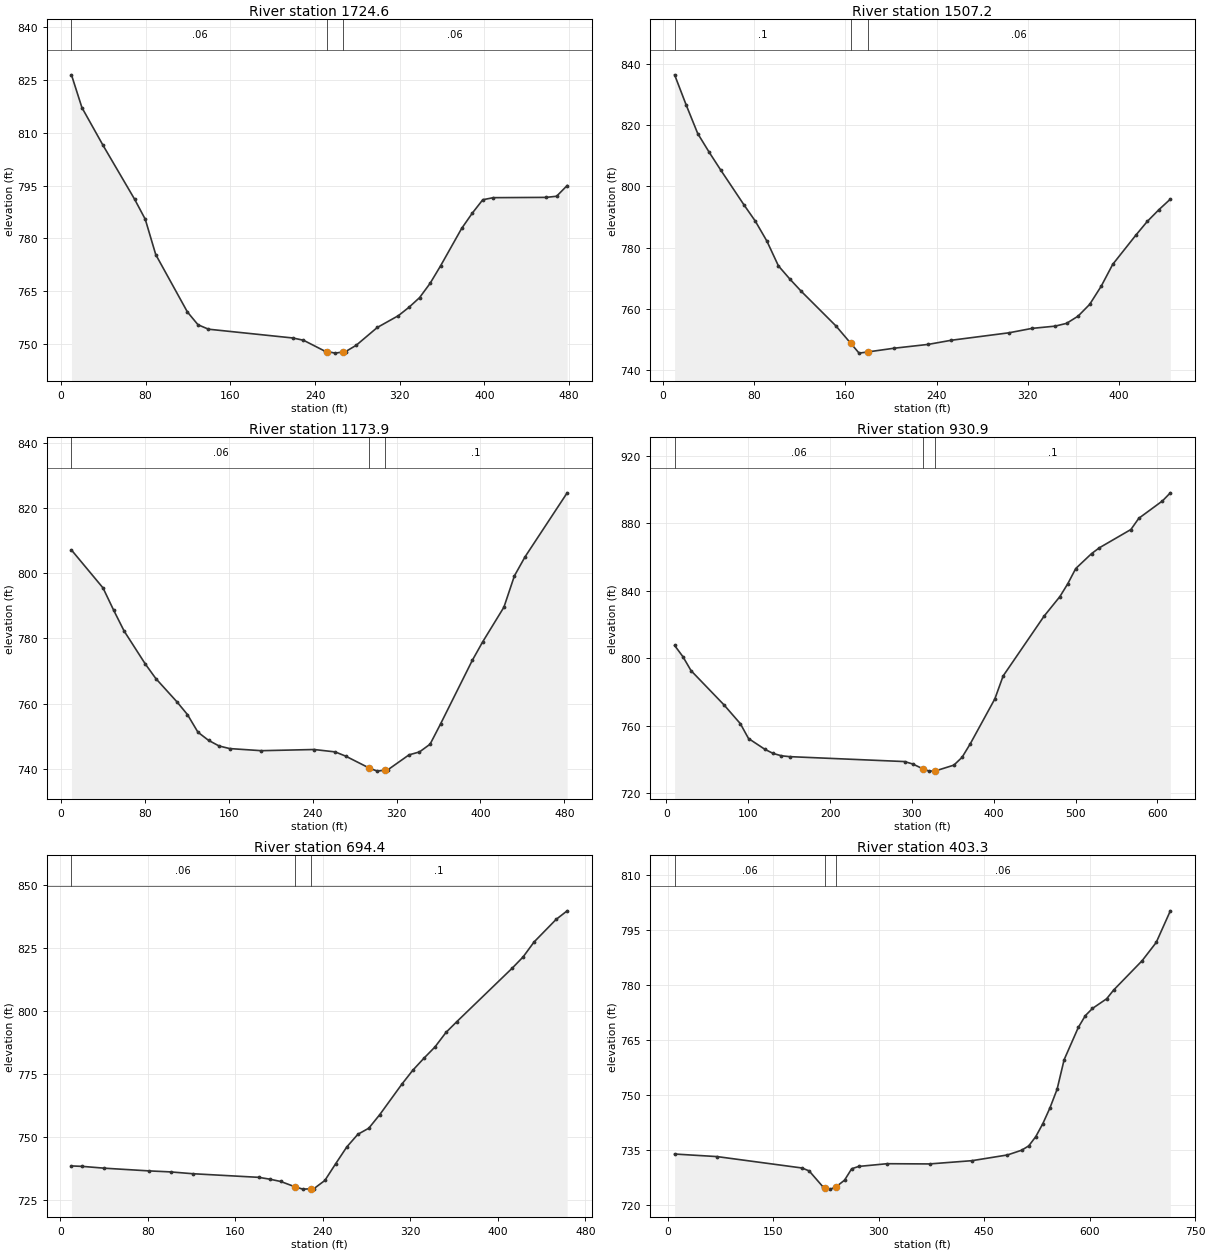
Type RM Length L Ch R = 1 ,1724.6  ,228.4,217.4,206.3
XS GIS Cut Line= 2
     1628203.226      286478.678     1627734.719      286383.354
#Sta/Elev= 30
      10  826.46    19.9  817.14    39.8  806.44    69.7  791.08    79.7  785.42
    89.6  775.38   119.5  759.08   129.5  755.45   139.4  754.19   219.1  751.69
   229.1  751.05     249     748   251.5  747.85     259  747.39   266.5  747.72
   268.9  747.83   278.9  749.62   298.8  754.68   318.7  758.03   328.7  760.41
   338.7  763.15   348.6  767.19   358.6  772.21   378.5  782.84   388.5  787.16
   398.4  790.97   408.4  791.56   458.2  791.64   468.1  791.96   478.1  795.01
#Mann= 3 , 0 , 0
      10     .06       0   251.5    .045       0   266.5     .06       0
Bank Sta=251.5,266.5
XS Rating Curve= 0 ,0
Exp/Cntr=0.3,0.1

Type RM Length L Ch R = 1 ,1507.2  ,333.2,333.3,333.6
XS GIS Cut Line= 2
     1628180.916      286176.481     1627749.257      286285.373
#Sta/Elev= 30
    10.1  836.54    20.2  826.72    30.4  817.31    40.5  811.17    50.6  805.36
    70.8  794.08    80.9  788.68    91.1  782.12   101.2  774.02   111.3  769.68
   121.4  765.64   151.8  754.32   164.5  748.76     172  745.46   179.5  745.84
   202.4  747.05   232.7  748.32   252.9  749.67   303.5  752.11   323.8  753.56
     344  754.29   354.1   755.2   364.2  757.56   374.4  761.42   384.5  767.35
   394.6   774.5   414.8  784.01   424.9  788.54   435.1  792.38   445.2  795.86
#Mann= 3 , 0 , 0
    10.1      .1       0   164.5    .045       0   179.5     .06       0
Bank Sta=164.5,179.5
XS Rating Curve= 0 ,0
Exp/Cntr=0.3,0.1

Type RM Length L Ch R = 1 ,1173.9  ,231.7,243,254.3
XS GIS Cut Line= 2
     1628107.741      285883.115     1627643.452      286015.197
#Sta/Elev= 30
    10.1  807.09    40.2  795.47    50.3  788.67    60.3  782.28    80.5  772.18
    90.5  767.73   110.6  760.61   120.7  756.68   130.7  751.28   140.8  748.79
   150.8  747.07   160.9  746.27   191.1  745.62   241.4  745.98   261.5  745.25
   271.5  743.96   294.2  740.27   301.7  739.36   309.2  739.67   311.8  739.78
   331.9  744.34   341.9  745.24     352  747.61     362  753.82   392.2  773.26
   402.3  779.04   422.4  789.58   432.4  799.17   442.5  804.98   482.7   824.6
#Mann= 3 , 0 , 0
    10.1     .06       0   294.2    .045       0   309.2      .1       0
Bank Sta=294.2,309.2
XS Rating Curve= 0 ,0
Exp/Cntr=0.3,0.1

Type RM Length L Ch R = 1 ,930.9   ,252.6,236.5,220.5
XS GIS Cut Line= 3
     1628142.381      285797.214     1627692.128      285695.805
     1627554.212      285764.763
#Sta/Elev= 30
      10  807.61    20.1     801    30.1  792.68    70.2   772.5    90.3  761.31
   100.3  752.51   120.4  746.08   130.4  743.68   140.5  742.28   150.5  741.78
     291  738.86     301  737.41   313.6  734.52   321.1   733.2   328.6  733.32
   351.2  736.75   361.2  741.37   371.2  749.35   401.3  776.01   411.4  789.55
   461.5  825.02   480.8  836.59   490.4  844.17   500.1  853.15   519.4  861.98
     529  865.45   567.5  876.27   577.2  882.93   606.1  893.21   615.7  897.99
#Mann= 3 , 0 , 0
      10     .06       0   313.6    .045       0   328.6      .1       0
Bank Sta=313.6,328.6
XS Rating Curve= 0 ,0
Exp/Cntr=0.3,0.1

Type RM Length L Ch R = 1 ,694.4   ,285.3,291.1,296.8
XS GIS Cut Line= 2
     1628034.888      285399.693     1627622.492      285610.963
#Sta/Elev= 30
    10.1   738.4    20.1  738.22    40.3   737.5    80.6  736.44   100.7  736.03
   120.9  735.31   181.3  733.87   191.4  733.15   201.5  732.22   214.1  730.18
   221.6  729.19   229.1  729.31   231.7  729.35   241.8  732.62   251.8  739.34
   261.9  745.95     272  750.96     282  753.38   292.1  758.81   312.3   770.9
   322.3  776.42   332.4  781.16   342.5  785.63   352.6  791.41   362.6  795.73
     413  816.86   423.1  821.38   433.1   827.3   453.3  836.28   463.4  839.68
#Mann= 3 , 0 , 0
    10.1     .06       0   214.1    .045       0   229.1      .1       0
Bank Sta=214.1,229.1
XS Rating Curve= 0 ,0
Exp/Cntr=0.3,0.1

Type RM Length L Ch R = 1 ,403.3   ,146,161.4,176.7
XS GIS Cut Line= 2
     1627946.219      285185.761     1627247.959      285338.848
#Sta/Elev= 30
    10.1  733.86    70.5  733.16   191.3  730.05   201.4  729.25   221.5   724.8
   224.1  724.67   231.6  724.29   239.1  724.84   251.7  726.74   261.8  729.84
   271.8  730.48   312.1  731.22   372.5  731.16   432.9  732.05   483.3  733.61
   503.4   734.9   513.5  736.08   523.5   738.6   533.6  742.17   543.7  746.46
   553.8  751.51   563.8  759.57     584  768.39     594   771.6   604.1  773.56
   624.2  776.18   634.3  778.59   674.6  786.55   694.7  791.54   714.8  800.17
#Mann= 3 , 0 , 0
    10.1     .06       0   224.1    .045       0   239.1     .06       0
Bank Sta=224.1,239.1
XS Rating Curve= 0 ,0
Exp/Cntr=0.3,0.1

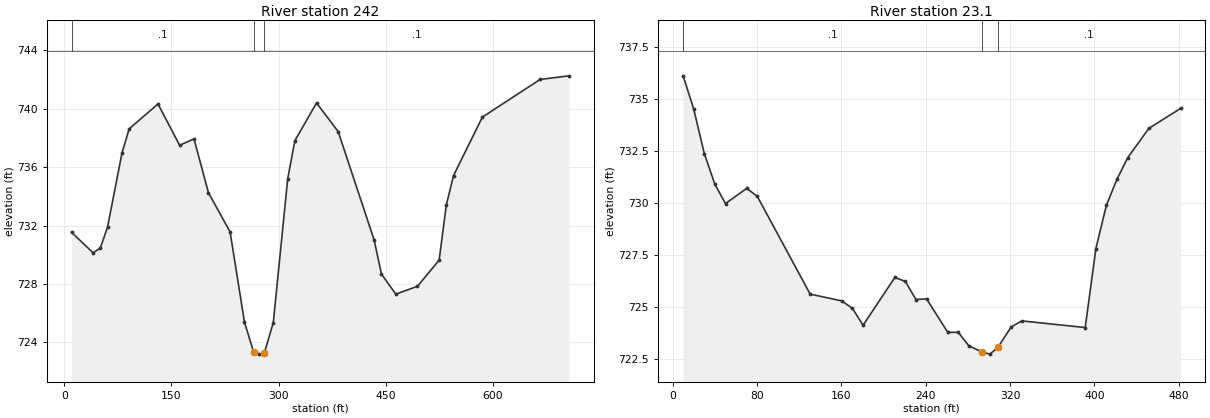
Type RM Length L Ch R = 1 ,242     ,219.2,218.8,218.5
XS GIS Cut Line= 3
     1627935.508      285168.482     1627566.317      285032.771
     1627286.494      284892.651
#Sta/Elev= 30
    10.1  731.54    40.3  730.13    50.4  730.46    60.5  731.89    80.7  736.97
    90.8  738.63   131.1  740.33   161.4   737.5   181.5  737.94   201.7  734.25
     232  731.57   252.1  725.39   264.8  723.36   272.3  723.19   279.8  723.24
   292.5  725.35   312.7  735.22   322.7  737.82     353   740.4   383.3  738.44
   433.7     731   443.8  728.68     464   727.3   494.3  727.84   524.6  729.63
   534.7  733.42   544.8  735.43   585.1  739.43   665.9  742.01   706.3  742.26
#Mann= 3 , 0 , 0
    10.1      .1       0   264.8    .045       0   279.8      .1       0
#XS Ineff= 2 , 0
       0     131             353       0
Permanent Ineff=
       F       F
Bank Sta=264.8,279.8
XS Rating Curve= 0 ,0
Exp/Cntr=0.3,0.1

Type RM Length L Ch R = 1 ,23.1    ,35.9,23.1,10.4
XS GIS Cut Line= 2
     1627941.592      284979.862     1627497.424      284793.271
#Sta/Elev= 30
      10  736.12    20.1  734.51    30.1  732.37    40.1   730.9    50.2  729.97
    70.3   730.7    80.3  730.32   130.5  725.61   160.6  725.28   170.6  724.92
   180.7  724.11   210.8  726.41   220.8  726.22   230.8  725.35   240.9  725.38
     261  723.77     271  723.77     281  723.12   293.6  722.82   301.1  722.72
   308.6  723.05   321.2  724.03   331.2  724.32   391.4     724   401.5   727.8
   411.5  729.89   421.5  731.14   431.6  732.17   451.7  733.59   481.8  734.55
#Mann= 3 , 0 , 0
      10      .1       0   293.6    .045       0   308.6      .1       0
#XS Ineff= 2 , 0
       0     255             331       0
Permanent Ineff=
       F       F
Bank Sta=293.6,308.6
XS Rating Curve= 0 ,0
Exp/Cntr=0.3,0.1

Chan Stop Cuts=-1
Use User Specified Reach Order=0